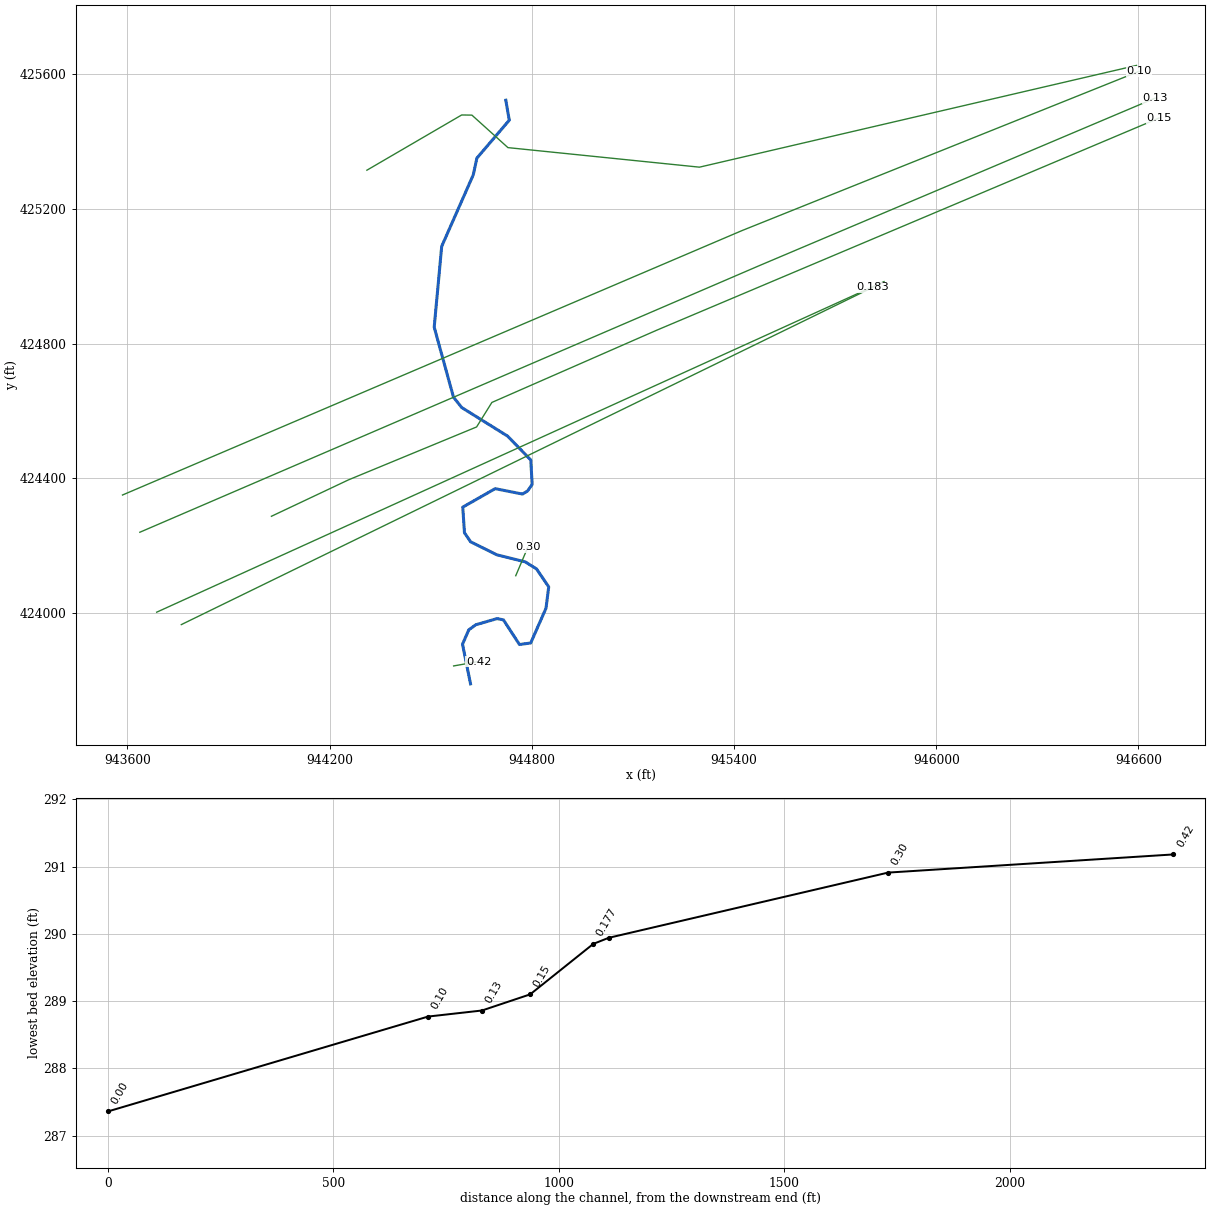
--- Haywood213.prj (project) ---

Proj Title=Haywood213
Current Plan=p01
Default Exp/Contr=0.3,0.1
English Units
Geom File=g01
Geom File=g03
Geom File=g06
Geom File=g07
Flow File=f01
Plan File=p02
Plan File=p03
Plan File=p06
Plan File=p07
Plan File=p01
Y Axis Title=Elevation
X Axis Title(PF)=Main Channel Distance
X Axis Title(XS)=Station
BEGIN DESCRIPTION:
END DESCRIPTION:
DSS Export Rating Curves= 0
DSS Export Rating Curve Sorted= 0
DSS Export Volume Flow Curves= 0
DXF Filename=..\HaywoodSetup.
DXF OffsetX= 0
DXF OffsetY= 0
DXF ScaleX= 1
DXF ScaleY= 10

--- Haywood213.p01 (plan) ---

Plan Title=Proposed-CorrectedSSdepth
Program Version=4.10
Short Identifier=Proposed-Revised
Geom File=g06
Flow File=f01
Subcritical Flow
K Sum by GR= 0
Std Step Tol= 0.01
Critical Tol= 0.01
Num of Std Step Trials= 20
Max Error Tol= 0.3
Flow Tol Ratio= 0.001
Split Flow NTrial= 30
Split Flow Tol= 0.02
Split Flow Ratio= 0.02
Log Output Level= 0
Friction Slope Method= 1
Unsteady Friction Slope Method= 2
Unsteady Bridges Friction Slope Method= 1
Parabolic Critical Depth
Global Vel Dist= 0 , 0 , 0
Global Log Level= 0
CheckData=True
Encroach Param=-1 ,0,0, 0
Computation Interval=1HOUR
Output Interval=1HOUR
Run HTab= 0
Run UNet= 0
Run PostProcess= 0
Run WQNet= 0
UNET Theta= 1
UNET Theta Warmup= 1
UNET ZTol= 0.02
UNET ZSATol= 0.05
UNET MxIter= 20
UNET MaxInSteps= 0
UNET DtIC= 0
UNET DtMin= 0
UNET MaxCRTS= 20
UNET WFStab= 2
UNET SFStab= 1
UNET WFX= 1
UNET SFX= 1
UNET DSS MLevel= 4
UNET DZMax Abort= 100
UNET Convert EG Bridges= 0
UNET Use Existing IB Tables=-1
UNET Froude Reduction=False
UNET Froude Limit= 1
UNET Froude Power= 10
UNET Time Slicing=0,0, 5
UNET Junction Losses=0
Instantaneous Interval=1HOUR
Write IC File= 0
Write IC File at Sim End=0
Echo Input=False
Echo Parameters=False
Echo Output=False
Write Detailed= 0
WQ AD Non Conservative
WQ ULTIMATE=-1
WQ Max Comp Step=1HOUR
WQ Output Interval=15MIN
WQ Output Selected Increments= 0
WQ Output face flow=0
WQ Output face velocity=0
WQ Output face area=0
WQ Output face dispersion=0
WQ Output cell volume=0
WQ Output cell surface area=0
WQ Output cell continuity=0
WQ Output cumulative cell continuity=0
WQ Output face conc=0
WQ Output face dconc_dx=0
WQ Output face courant=0
WQ Output face peclet=0
WQ Output face adv mass=0
WQ Output face disp mass=0
WQ Output cell mass=0
WQ Output cell source sink temp=0
WQ Output cell source sink nsm=0
WQ Output MaxMinRange=-1
WQ Daily Max Min Mean=-1
WQ Daily Range=0
WQ Daily Time=0
WQ Create Restart=0
WQ Fixed Restart=0
WQ System Summary=0
WQ Use Fixed Temperature=0
Sorting and Armoring Iterations= 10
XS Update Threshold= 0.02
Hydraulics Update Threshold= 0.02
Energy Slope Method= 1
Volume Change Method= 0
XS Weighting Method= 0
Number of US Weighted Cross Sections= 1
Number of DS Weighted Cross Sections= 1
Upstream XS Weight=0.25
Main XS Weight=0.5
Downstream XS Weight=0.25
Number of DS XS's Weighted with US Boundary= 1
Upstream Boundary Weight= 1
Weight of XSs Associated with US Boundary= 0
Number of US XS's Weighted with DS Boundary= 1
Downstream Boundary Weight= 0.5
Weight of XSs Associated with DS Boundary= 0.5
Sediment Output Level= 4
Mass or Volume Output= 0
Output Increment Type= 1
Profile and TS Output Increment= 10
XS Output Flag= 0
XS Output Increment= 10
Disregard all LS=0
Disregard all Conn=0
Disregard all Breaches=0
Disregard all Pumps=0

--- Haywood213.p02 (plan) ---

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Plan Title=Natural
Short Identifier=Natural
Geom File=g01
Flow File=f01

--- Haywood213.p03 (plan) ---

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Plan Title=Diversion Pipe Sizing
Short Identifier=DiversionPipe
Geom File=g03
Flow File=f01

--- Haywood213.p06 (plan) ---

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Plan Title=Proposed
Short Identifier=Proposed
Geom File=g06
Flow File=f01

--- Haywood213.p07 (plan) ---

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Plan Title=Existing
Short Identifier=Existing
Geom File=g07
Flow File=f01

--- Haywood213.f01 (steady flow) ---

Flow Title=Flowrates
Program Version=4.10
Number of Profiles= 7
Profile Names=2 Yr,5 Yr,10 Yr,25 Yr,50 Yr,100 Yr,500 Yr
River Rch & RM=Stream,Reach           ,0.42
    1100    1610    1950    2370    2670    2970    3670
Boundary for River Rch & Prof#=Stream,Reach           , 1
Up Type= 0
Dn Type= 3
Dn Slope=0.002
Boundary for River Rch & Prof#=Stream,Reach           , 2
Up Type= 0
Dn Type= 3
Dn Slope=0.002
Boundary for River Rch & Prof#=Stream,Reach           , 3
Up Type= 0
Dn Type= 3
Dn Slope=0.002
Boundary for River Rch & Prof#=Stream,Reach           , 4
Up Type= 0
Dn Type= 3
Dn Slope=0.002
Boundary for River Rch & Prof#=Stream,Reach           , 5
Up Type= 0
Dn Type= 3
Dn Slope=0.002
Boundary for River Rch & Prof#=Stream,Reach           , 6
Up Type= 0
Dn Type= 3
Dn Slope=0.002
Boundary for River Rch & Prof#=Stream,Reach           , 7
Up Type= 0
Dn Type= 3
Dn Slope=0.002
DSS Import GetInterval= 0
DSS Import GetPeak= 0
DSS Import FillOption= 0

--- Haywood213.g06 (geometry) ---

Geom Title=Proposed
Program Version=4.10

River Reach=Stream          ,Reach
Reach XY= 30
    944618.30077 423790.63420573 944594.52783313 423908.12699151
  944613.1106479 423950.83183345 944634.01631452 423965.93830815
 944697.31402733 423984.24038326  944715.8968421 423980.46376459
 944763.51530495 423907.25546413 944796.90630024 423911.90361019
 944842.20191124 424014.74384179  944850.3318927   424078.365341
  944814.0201013 424131.68142267 944780.64633731 424152.44516884
 944696.44295789 424173.36182612 944618.62742104 424211.99954025
 944600.33496275  424238.7263801 944595.26591704 424314.76799567
  944691.3557649 424369.55231093 944772.73113146 424353.57875542
 944787.46672286 424362.72979297 944801.18606657 424382.04865004
 944797.03811685 424454.62405561 944728.57376548 424525.21968011
 944592.18687825   424610.221333 944567.73157931 424640.99555198
 944510.51301241  424848.5762072 944532.77853583  425088.3586037
 944626.41331595 425300.34467129 944637.15650574 425350.02173231
 944733.25931594 425462.51361095 944722.95684581 425521.73597193

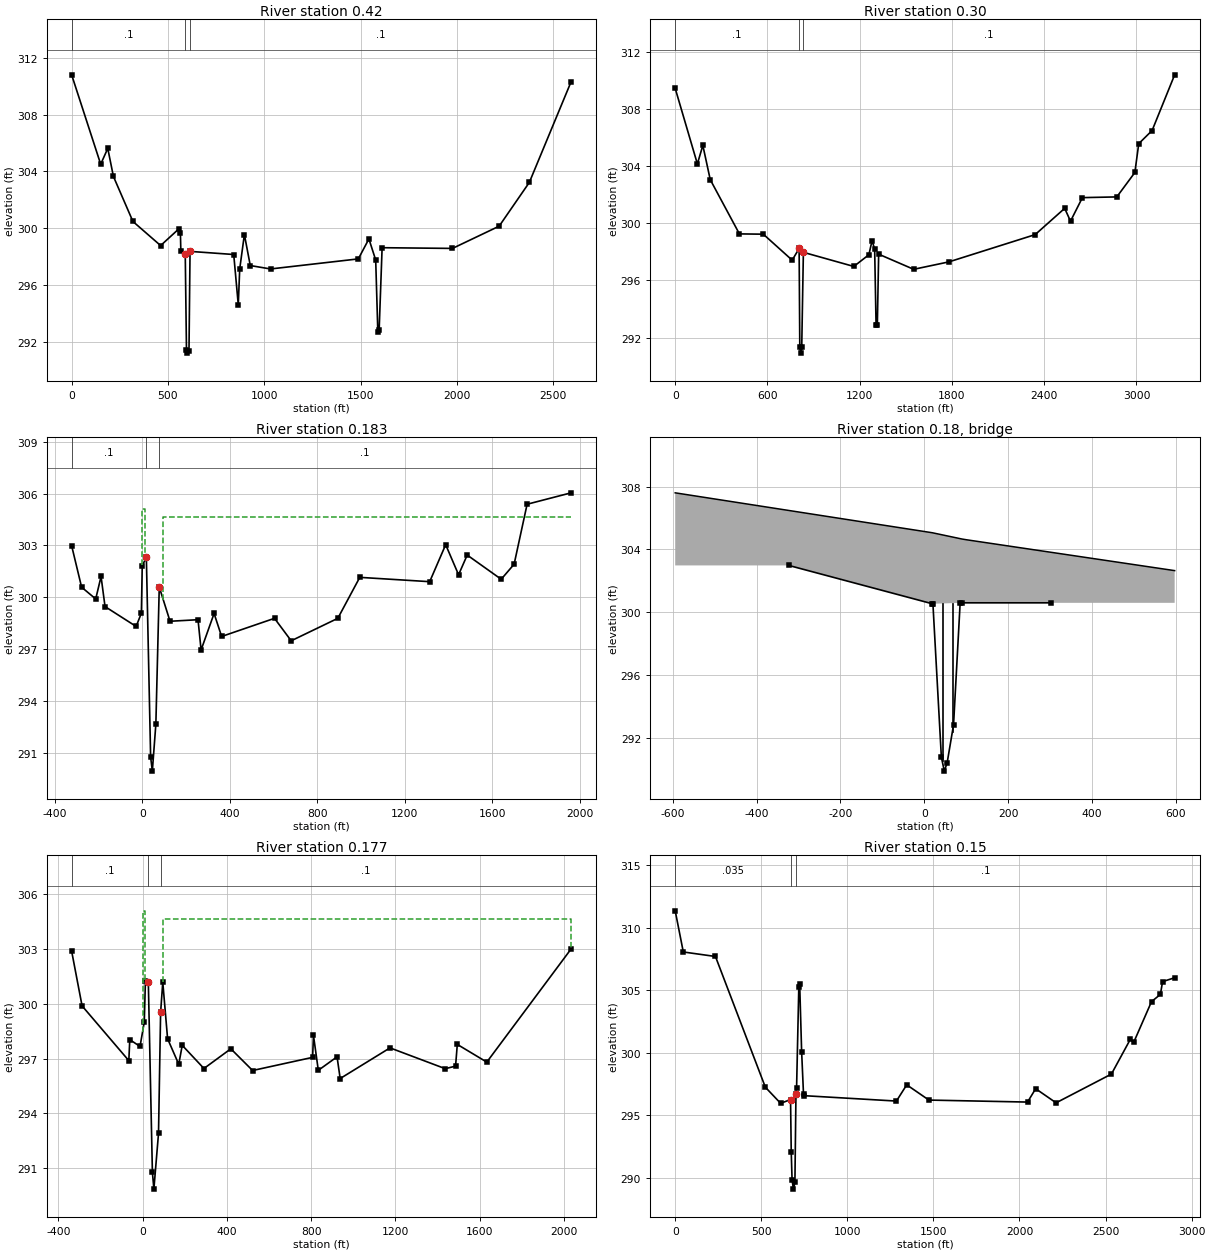
Type RM Length L Ch R = 1 ,0.42    ,420,633,608
XS GIS Cut Line= 2
       944568.11       423843.76       944641.97       423856.78
#Sta/Elev= 30
       0  310.82   150.8  304.51   187.5  305.63  216.75  303.65  318.08  300.47
  461.85  298.77  558.07  299.97  564.52  299.65  566.68  298.38  589.58  298.17
  595.99  291.37  601.13  291.18  608.99  291.32  614.44  298.36  841.17  298.14
  864.78  294.59  872.23  297.12  896.48  299.55  927.01  297.36 1032.23  297.12
 1487.73  297.83 1542.71  299.24 1577.91  297.75 1588.96   292.7 1595.86  292.82
 1611.22  298.62 1976.48  298.57 2218.62  300.14  2375.3  303.23 2591.86  310.33
#Mann= 3 , 0 , 0
       0      .1       0  589.58     .03       0  614.44      .1       0
Bank Sta=589.58,614.44
XS Rating Curve= 0 ,0
Exp/Cntr=0.3,0.1

Type RM Length L Ch R = 1 ,0.30    ,360,620,390
XS GIS Cut Line= 2
       944752.46       424111.34       944788.41       424196.03
#Sta/Elev= 30
       0  309.45  144.26  304.16  179.68  305.46  227.85  303.06  417.51  299.26
  572.86  299.24  760.73  297.42  805.88  298.24  810.28  291.32  817.68  290.91
  822.83  291.33  833.56  297.97 1161.51  296.98  1259.6   297.8 1280.25  298.79
 1297.14  298.19 1306.37  292.86 1314.55  292.89 1323.16  297.84 1550.95  296.78
 1779.91   297.3 2341.02  299.21    2533  301.05 2570.79  300.15 2648.15   301.8
 2871.93  301.85 2989.33  303.56 3014.61  305.58  3101.5   306.5  3248.1   310.4
#Mann= 3 , 0 , 0
       0      .1       0  805.88     .03       0  833.56      .1       0
Bank Sta=805.88,833.56
XS Rating Curve= 0 ,0
Exp/Cntr=0.3,0.1

Type RM Length L Ch R = 1 ,0.183   ,34,34,34
XS GIS Cut Line= 4
943760.223292774423966.352623747       944741.29       424444.77
       944831.17        424488.6945812.236707226424967.017376254
#Sta/Elev= 30
  -323.4  302.98 -277.82  300.58 -213.33   299.9 -188.94   301.2 -170.76  299.46
  -28.58  298.31    -4.6  299.08    -.69  301.83   18.13   302.3   37.67  290.76
   45.44  289.94    61.6  292.66   77.15  300.59  126.35  298.61   254.3   298.7
  268.36  296.95  327.75  299.06  362.19  297.73  603.91  298.78  680.18  297.48
  893.31  298.78  993.73  301.15 1313.31   300.9 1386.36  303.04 1445.33   301.3
 1484.77  302.44  1640.2  301.04 1699.21  301.91 1758.61  305.38  1959.6  306.04
#Mann= 3 , 0 , 0
  -323.4      .1       0   18.13     .03       0   77.15      .1       0
#XS Ineff= 2 , 0
       0   10.22   305.1    96.2       0  304.63
Permanent Ineff=
       F       F
Bank Sta=18.13,77.15
XS Rating Curve= 0 ,0
Exp/Cntr=0.5,0.3

Type RM Length L Ch R = 3 ,0.18    ,,,
Bridge Culvert--1,0,-1,-1, 0
Deck Dist Width WeirC Skew NumUp NumDn MinLoCord MaxHiCord MaxSubmerge Is_Ogee
10.5,14,2.6,0, 6, 6, , , 0.98, 0, 0,0,,
  -594.2       0   19.26   90.18  101.69   597.5
   307.6  305.14  305.06  304.66  304.61  302.65
                  300.54   300.6
  -594.2       0   19.26   90.18  101.69   597.5
   307.6  305.14  305.06  304.66  304.61  302.65
                  300.54   300.6
Pier Skew, UpSta & Num, DnSta & Num=  ,42.89, 4 ,42.89, 4 , 3 , 3 , 0 ,,
    1.08    1.08     2.8     2.8
     290  297.35  297.35     301
    1.08    1.08     2.8     2.8
     290  297.35  297.35     301
Pier Skew, UpSta & Num, DnSta & Num=  ,66.89, 4 ,66.89, 4 , 3 , 3 , 0 ,,
    1.08    1.08     2.8     2.8
     290  297.35  297.35     301
    1.08    1.08     2.8     2.8
     290  297.35  297.35     301
BR Coef=-1 , 1 , 1 ,0.9, 0 ,,,0.8,0,1.2,0,
WSPro=,,,, 1 ,,,, 0 ,,,, 0 ,,,,-1 ,-1 ,-1 , 0 , 0 , 0 , 0 , 0
BR U #Sta/Elev= 10
  -323.4  302.98   19.26  300.54   20.72  300.54   40.88  290.78   47.96  289.89
   54.74  290.43   69.94  292.84    85.7   300.6   90.18   300.6  302.65   300.6
BR U #Mann= 2
  -323.4      .1   19.26    .035
BR U Banks=20.72,85.7
BR D #Sta/Elev= 10
  -323.4  302.98   19.26  300.54   20.72  300.54   40.88  290.78   47.96  289.89
   54.74  290.43   69.94  292.84    85.7   300.6   90.18   300.6  302.65   300.6
BR D #Mann= 2
  -323.4      .1   19.26   .0351
BR D Banks=20.72,85.7
BC Design=,, 0 ,, 0 ,,,,,,
BC Use User HTab Curves=0
BC User HTab FreeFlow(D)= 0

Type RM Length L Ch R = 1 ,0.177   ,115,140,162
XS GIS Cut Line= 4
943687.133377281424003.186149623       944721.18       424473.04
       944811.06       424513.88945845.106622719424983.733850377
#Sta/Elev= 30
 -336.44  302.89 -286.88  299.89  -65.03  296.89   -60.5  298.04  -11.88  297.67
    8.28     299    13.7  301.26   27.54  301.19   46.85  290.77   53.86  289.85
   75.85   292.9   85.81  299.53   96.08  301.19  118.96  298.09  171.95  296.69
  188.45  297.73  291.49  296.46  419.09  297.54  522.42  296.35  807.16  297.07
  811.29  298.27  834.26  296.36  923.23   297.1  938.01  295.91 1174.53  297.59
 1436.66  296.45 1485.65  296.59 1493.86  297.78 1633.87  296.81 2033.86  303.01
#Mann= 3 , 0 , 0
 -336.44      .1       0   27.54     .03       0   85.81      .1       0
#XS Ineff= 2 , 0
       0    13.7   305.1   96.08       0  304.63
Permanent Ineff=
       F       F
Bank Sta=27.54,85.81
XS Rating Curve= 0 ,0
Exp/Cntr=0.5,0.3

Type RM Length L Ch R = 1 ,0.15    ,120,106.95,65
XS GIS Cut Line= 6
  944027.5663263  424287.6785177  944256.2689892  424395.7151194
  944636.3349828  424552.6591568  944681.6714252  424625.3499879
    945169.08922  424838.8741975  946660.8549566  425468.8152385
#Sta/Elev= 30
       0  311.35   47.04  308.06   233.8   307.7  523.56  297.25  612.39  295.96
  670.02  296.26  674.02  292.07  678.89  289.83  687.01   289.1  695.35  289.63
  701.47  296.71  705.09   297.2  717.96  305.23   723.1  305.47  734.39   300.1
  745.27   296.7   750.7  296.57 1285.04  296.14 1344.89  297.44 1473.79  296.22
 2046.78  296.06 2093.85  297.13 2212.51     296 2534.07   298.3 2644.28  301.09
 2663.27  300.83 2766.85  304.09 2818.55  304.67 2831.12  305.69 2901.26     306
#Mann= 3 , 0 , 0
       0    .035       0  670.02     .03       0  701.47      .1       0
#XS Ineff= 2 , 0
       0   515.4          720.27       0
Permanent Ineff=
       F       F
Bank Sta=670.02,701.47
XS Rating Curve= 0 ,0
Exp/Cntr=0.5,0.3

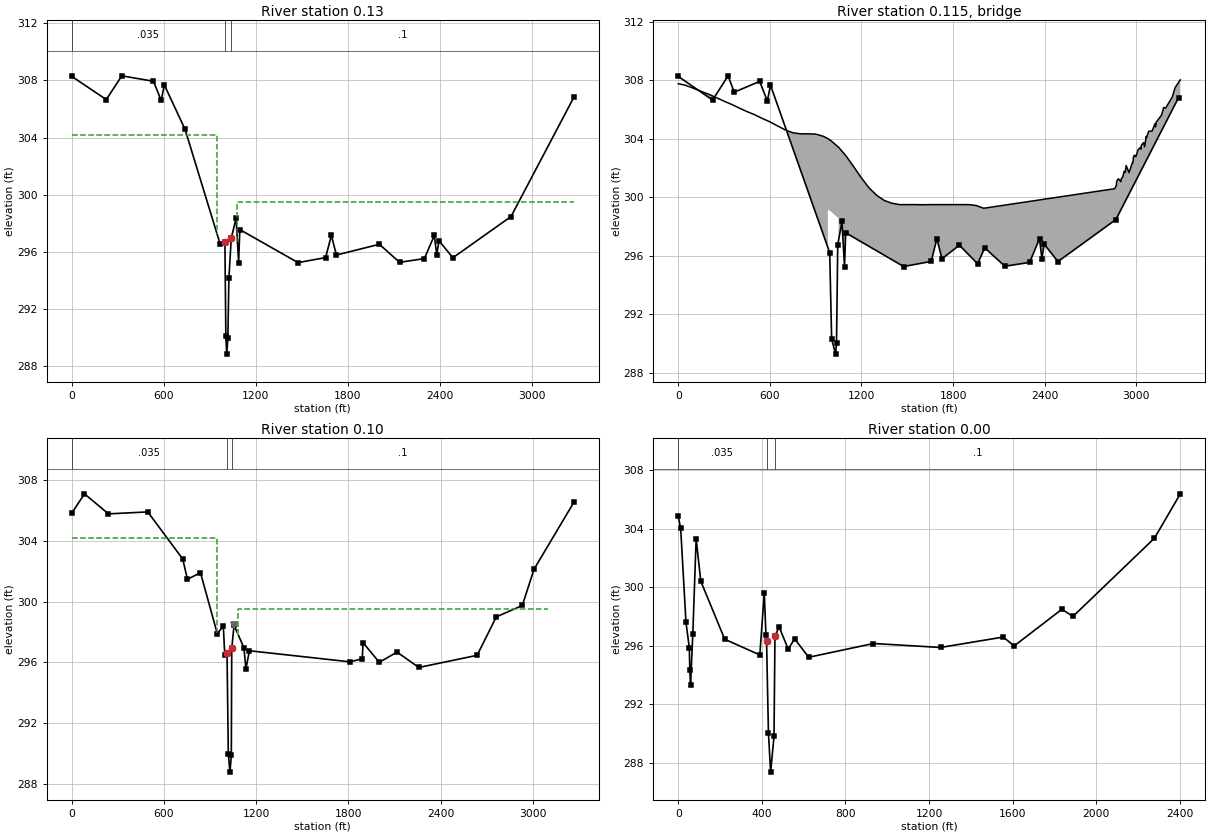
Type RM Length L Ch R = 1 ,0.13    ,119.5,119.51,119.5
XS GIS Cut Line= 3
   943637.152646  424240.3162534  945475.8734474   425031.442915
  946649.4179144  425527.9685264
#Sta/Elev= 30
       0  308.28  225.23  306.66   326.3  308.32  533.21  307.94  583.31   306.6
  604.14  307.68  739.47  304.57  967.13  296.59  999.14  296.73 1005.33  290.14
 1011.18  288.86 1018.27  289.96 1025.22  294.16 1040.73  296.98 1072.13  298.35
 1088.76  295.26 1096.52  297.57 1476.22  295.26 1656.49  295.61 1693.71  297.17
  1726.9  295.79    2007  296.54 2139.04  295.28 2300.63  295.54 2365.66  297.16
 2381.44   295.8 2396.09  296.79 2486.64   295.6 2866.02  298.48 3275.96  306.82
#Mann= 3 , 0 , 0
       0    .035       0  999.14     .03       0 1040.73      .1       0
#XS Ineff= 2 , 0
       0     948   304.2    1081       0   299.5
Permanent Ineff=
       F       F
Bank Sta=999.14,1040.73
XS Rating Curve= 0 ,0
Exp/Cntr=0.5,0.3

Type RM Length L Ch R = 3 ,0.115   ,,,
Bridge Culvert--1,-1,-1,-1, 0
Deck Dist Width WeirC Skew NumUp NumDn MinLoCord MaxHiCord MaxSubmerge Is_Ogee
29,37.25,2.6,0, 106, 106, , , 0.98, 0, 0,0,,
       0   49.51   49.73  100.23  100.32   100.4  123.16  150.52  200.03  200.09
  249.82  250.32  250.83  300.43   300.6  350.26  400.24  400.28  400.31  450.34
  500.26  500.29  503.38  550.32  550.76     600     650     700     750     800
     850     900     950  979.78  979.78    1000 1049.78 1049.78    1050    1100
    1150    1200    1250    1300    1350    1400 1400.33 1449.61 1450.25  1500.1
 1500.27 1550.15 1550.31 1600.19 1600.33 1650.18 1650.28 1650.39 1701.64 1701.72
 1720.98 1750.34 1750.47  1800.5 1800.96 1850.33 1850.56 1901.62 1902.19 1949.92
    2000 2858.28 2868.64 2871.26 2882.16 2898.78 2899.94 2912.22 2920.15 2926.88
 2933.28 2951.74 2973.95 2977.34 2980.24 2986.58 2997.12 3010.55 3024.19 3029.79
 3032.53 3047.57 3053.63 3064.69 3066.35  3080.4 3103.22 3121.89 3124.87 3131.28
 3163.83 3178.69 3191.32 3234.62 3253.57 3287.69
  307.78  307.67  307.66  307.47  307.46  307.46  307.37  307.25  307.06  307.06
  306.82  306.82  306.82  306.58  306.58  306.36  306.11  306.11  306.11  305.87
  305.66  305.66  305.64   305.4   305.4  305.17  304.89  304.62  304.42  304.35
  304.35  304.33  304.18  304.02  304.02  303.88  303.43  303.43  303.43  302.82
  302.08  301.32  300.64  300.13  299.78  299.59  299.59   299.5   299.5   299.5
   299.5   299.5   299.5  299.49  299.49   299.5   299.5   299.5   299.5   299.5
   299.5   299.5   299.5   299.5   299.5   299.5   299.5   299.5   299.5  299.44
  299.25  300.59  300.81  301.11  301.27  301.07  301.23  301.45  301.78  301.71
  302.18  301.69  302.38  302.36  302.72  302.89  302.78  303.25   303.4   303.3
  303.57  303.75  303.46  304.17  304.08  304.52  304.54  305.05  304.82  305.17
  305.61  306.15  306.11  306.86  307.51  308.05
                                                                                
                                                                                
                                                                                
                               0  299.16  299.02  298.57       0
                                                                                
                                                                                
                                                                                
                                                                                
                                                                                
                                                                                
                                                
       0   49.51   49.73  100.23  100.32   100.4  123.16  150.52  200.03  200.09
  249.82  250.32  250.83  300.43   300.6  350.26  400.24  400.28  400.31  450.34
  500.26  500.29  503.38  550.32  550.76     600     650     700     750     800
     850     900     950  979.78  979.78    1000 1049.78 1049.78    1050    1100
    1150    1200    1250    1300    1350    1400 1400.33 1449.61 1450.25  1500.1
 1500.27 1550.15 1550.31 1600.19 1600.33 1650.18 1650.28 1650.39 1701.64 1701.72
 1720.98 1750.34 1750.47  1800.5 1800.96 1850.33 1850.56 1901.62 1902.19 1949.92
    2000 2858.28 2868.64 2871.26 2882.16 2898.78 2899.94 2912.22 2920.15 2926.88
 2933.28 2951.74 2973.95 2977.34 2980.24 2986.58 2997.12 3010.55 3024.19 3029.79
 3032.53 3047.57 3053.63 3064.69 3066.35  3080.4 3103.22 3121.89 3124.87 3131.28
 3163.83 3178.69 3191.32 3234.62 3253.57 3287.69
  307.78  307.67  307.66  307.47  307.46  307.46  307.37  307.25  307.06  307.06
  306.82  306.82  306.82  306.58  306.58  306.36  306.11  306.11  306.11  305.87
  305.66  305.66  305.64   305.4   305.4  305.17  304.89  304.62  304.42  304.35
  304.35  304.33  304.18  304.02  304.02  303.88  303.43  303.43  303.43  302.82
  302.08  301.32  300.64  300.13  299.78  299.59  299.59   299.5   299.5   299.5
   299.5   299.5   299.5  299.49  299.49   299.5   299.5   299.5   299.5   299.5
   299.5   299.5   299.5   299.5   299.5   299.5   299.5   299.5   299.5  299.44
  299.25  300.59  300.81  301.11  301.27  301.07  301.23  301.45  301.78  301.71
  302.18  301.69  302.38  302.36  302.72  302.89  302.78  303.25   303.4   303.3
  303.57  303.75  303.46  304.17  304.08  304.52  304.54  305.05  304.82  305.17
  305.61  306.15  306.11  306.86  307.51  308.05
                                                                                
                                                                                
                                                                                
                               0  299.16  299.02  298.57       0
                                                                                
                                                                                
                                                                                
                                                                                
                                                                                
                                                                                
                                                
BR Coef=-1 , 1 , 0 ,1.25, 0 ,,,0.8,0,2,0,
WSPro=,,,, 1 ,,,, 0 ,,,, 0 ,,,,-1 ,-1 ,-1 , 0 , 0 , 0 , 0 , 0
BR U #Sta/Elev= 30
       0  308.28  225.23  306.66   326.3  308.32  366.91   307.2  533.21  307.94
  583.31   306.6  604.14  307.68  991.83  296.21 1004.51  290.32 1029.98  289.26
 1036.38  289.99 1044.44  296.74 1072.13  298.35 1088.76  295.26 1096.52  297.57
 1476.22  295.26 1656.49  295.61 1693.71  297.17  1726.9  295.79 1840.89  296.72
 1960.51  295.45    2007  296.54 2139.04  295.28 2300.63  295.54 2365.66  297.16
 2381.44   295.8 2396.09  296.79 2486.64   295.6 2866.02  298.48 3275.96  306.82
BR U #Mann= 3
       0     .04  991.83    .035 1044.44      .1
BR U Banks=991.83,1044.44
BR D #Sta/Elev= 30
       0  305.82   82.78  307.09  238.67  305.77  494.45   305.9  752.73  301.46
  837.69   301.9  947.12  297.88  983.07  298.19  983.37  296.67  991.83  296.21
 1004.51  290.32 1014.51  290.32 1029.98  289.26 1036.38  289.99 1044.44  296.74
  1046.8  297.12 1066.35  298.32 1120.29  296.95 1133.15  295.57 1156.11  296.76
 1810.58  296.03 1890.21  296.23 1895.72  297.29 2001.07     296 2258.56  295.66
 2637.94  296.46 2762.59  298.99 2931.94  299.74 3007.83  302.12 3267.23  306.53
BR D #Mann= 3
       0     .04 1014.51    .035  1046.8      .1
BR D Banks=991.83,1044.44
BC Design=,, 0 ,, 0 ,,,,,,
BC Use User HTab Curves=0
BC User HTab FreeFlow(D)= 0

Type RM Length L Ch R = 1 ,0.10    ,770,710,610
XS GIS Cut Line= 3
  943585.7226802    424350.75119  945423.0667329  425134.7853974
  946601.4501164  425607.3151291
#Sta/Elev= 30
       0  305.82   82.78  307.09  238.67  305.77  494.45   305.9  722.04   302.8
  752.73  301.46  837.69   301.9  947.12  297.88  986.14  298.39  995.53  296.48
 1010.31  296.62 1018.65  289.98 1029.38  288.77 1038.27  289.87 1040.97  296.93
 1056.25  298.44 1120.29  296.95 1133.15  295.57 1156.11  296.76 1810.58  296.03
 1890.21  296.23 1895.72  297.29 2001.07     296 2116.86  296.67 2258.56  295.66
 2637.94  296.46 2762.59  298.99 2931.94  299.74 3007.83  302.12 3267.23  306.53
#Mann= 3 , 0 , 0
       0    .035       0 1010.31     .03       0 1040.97      .1       0
Levee=0,,,-1,1056.25,298.44,,
#XS Ineff= 3 ,-1
       0     946   304.2 1056.25    1084  298.44    1084    3100   299.5
Permanent Ineff=
       T       F       F
Bank Sta=1010.31,1040.97
XS Rating Curve= 0 ,0
Exp/Cntr=0.5,0.3

Type RM Length L Ch R = 1 ,0.00    ,0,0,0
XS GIS Cut Line= 6
  944310.8366914  425314.1710666  944592.0399092  425478.0240952
  944622.4007802  425477.5577836  944729.2984815  425381.1531821
  945297.4973842   425323.183646  946594.1221311  425624.9164289
#Sta/Elev= 30
       0  304.84   11.64  304.02   37.11  297.59   52.94  295.87   55.59  294.31
   58.88  293.33   69.82  296.83   85.67  303.31  107.92  300.41  222.53  296.44
   390.4  295.37  411.66  299.62  419.64  296.76   422.6  296.33  431.52  290.05
  442.07  287.36  458.19   289.8  462.78  296.63  482.49  297.29  526.07  295.77
  557.03  296.47  624.15  295.21  934.11  296.15 1255.11  295.88 1554.31  296.59
 1607.56  295.99 1835.68  298.49 1888.53     298 2278.51  303.35 2402.19  306.38
#Mann= 3 , 0 , 0
       0    .035       0   422.6     .03       0  462.78      .1       0
#XS Ineff= 2 , 0
       0   85.67  303.31               0
Permanent Ineff=
       F       F
Bank Sta=422.6,462.78
XS Rating Curve= 0 ,0
Exp/Cntr=0.3,0.1

Chan Stop Cuts=-1
Use User Specified Reach Order=0
Composite Channel Slope=5

--- Haywood213.g01 (geometry) ---

Geom Title=Natural
Program Version=4.10

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
River Reach=Stream          ,Reach

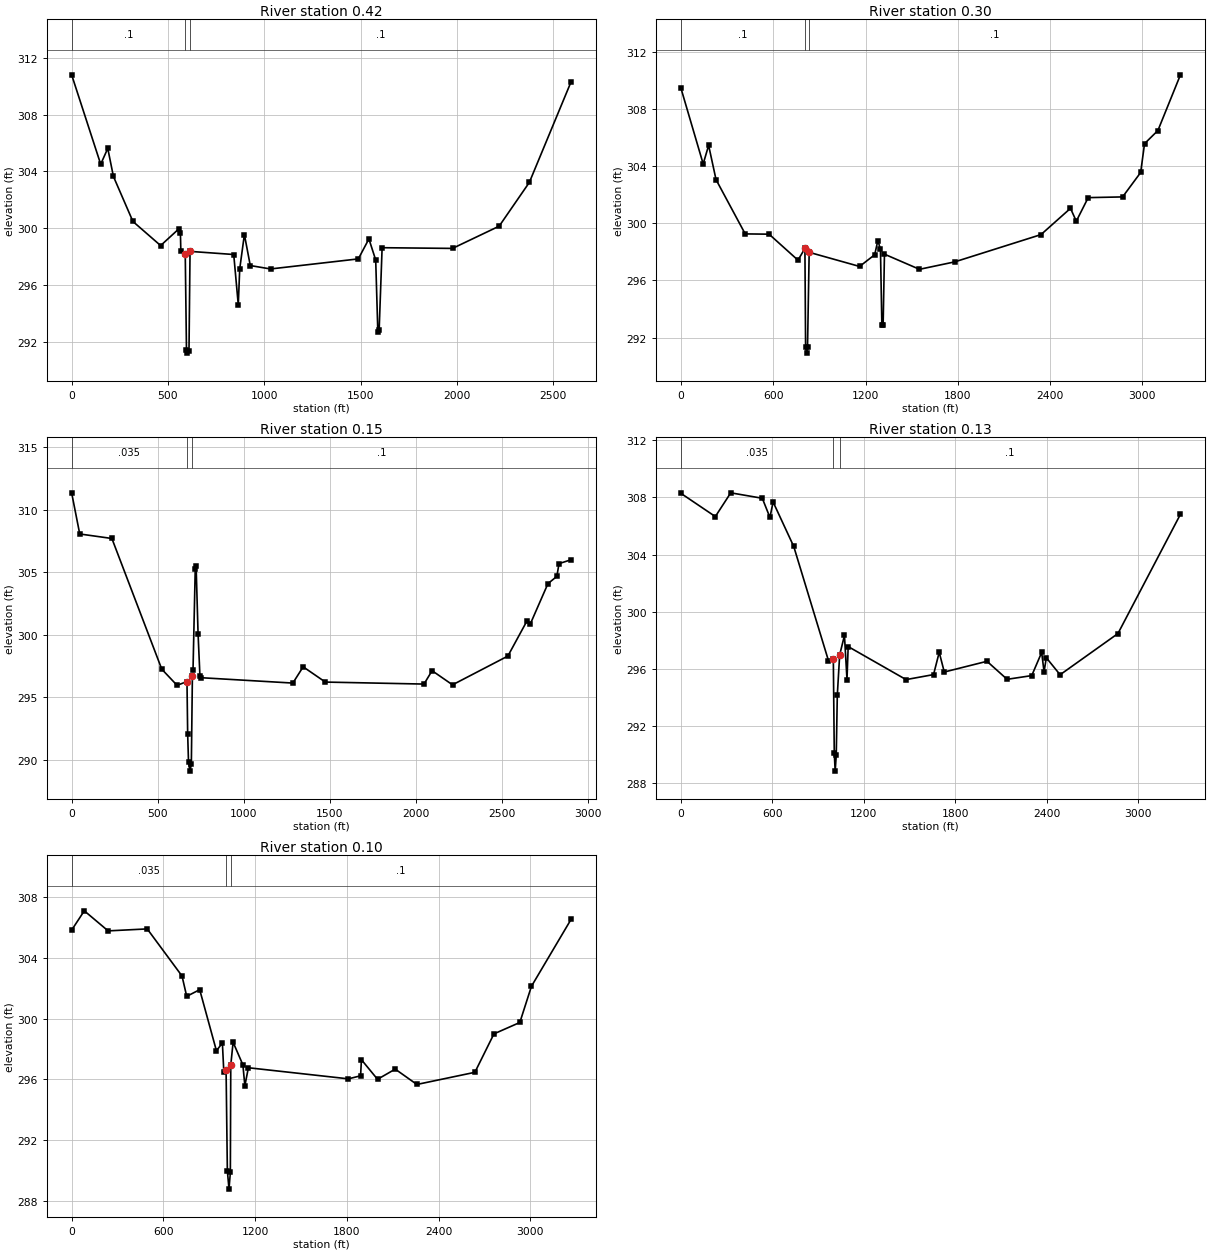
Type RM Length L Ch R = 1 ,0.42    ,420,633,608
XS GIS Cut Line= 2
       944568.11       423843.76       944641.97       423856.78
#Sta/Elev= 30
       0  310.82   150.8  304.51   187.5  305.63  216.75  303.65  318.08  300.47
  461.85  298.77  558.07  299.97  564.52  299.65  566.68  298.38  589.58  298.17
  595.99  291.37  601.13  291.18  608.99  291.32  614.44  298.36  841.17  298.14
  864.78  294.59  872.23  297.12  896.48  299.55  927.01  297.36 1032.23  297.12
 1487.73  297.83 1542.71  299.24 1577.91  297.75 1588.96   292.7 1595.86  292.82
 1611.22  298.62 1976.48  298.57 2218.62  300.14  2375.3  303.23 2591.86  310.33
#Mann= 3 , 0 , 0
       0      .1       0  589.58     .03       0  614.44      .1       0
#XS Ineff= 2 , 0
       0                  896.48       0  299.55
Permanent Ineff=
       F       F
Bank Sta=589.58,614.44
XS Rating Curve= 0 ,0
Exp/Cntr=0.3,0.1

Type RM Length L Ch R = 1 ,0.30    ,509,794,586
XS GIS Cut Line= 2
       944752.46       424111.34       944788.41       424196.03
#Sta/Elev= 30
       0  309.45  144.26  304.16  179.68  305.46  227.85  303.06  417.51  299.26
  572.86  299.24  760.73  297.42  805.88  298.24  810.28  291.32  817.68  290.91
  822.83  291.33  833.56  297.97 1161.51  296.98  1259.6   297.8 1280.25  298.79
 1297.14  298.19 1306.37  292.86 1314.55  292.89 1323.16  297.84 1550.95  296.78
 1779.91   297.3 2341.02  299.21    2533  301.05 2570.79  300.15 2648.15   301.8
 2871.93  301.85 2989.33  303.56 3014.61  305.58  3101.5   306.5  3248.1   310.4
#Mann= 3 , 0 , 0
       0      .1       0  805.88     .03       0  833.56      .1       0
#XS Ineff= 2 , 0
       0  572.86  299.24  833.56       0  297.97
Permanent Ineff=
       F       F
Bank Sta=805.88,833.56
XS Rating Curve= 0 ,0
Exp/Cntr=0.3,0.1

Type RM Length L Ch R = 1 ,0.15    ,120,106.95,65
XS GIS Cut Line= 6
  944027.5663263  424287.6785177  944256.2689892  424395.7151194
  944636.3349828  424552.6591568  944681.6714252  424625.3499879
    945169.08922  424838.8741975  946660.8549566  425468.8152385
#Sta/Elev= 30
       0  311.35   47.04  308.06   233.8   307.7  523.56  297.25  612.39  295.96
  670.02  296.26  674.02  292.07  678.89  289.83  687.01   289.1  695.35  289.63
  701.47  296.71  705.09   297.2  717.96  305.23   723.1  305.47  734.39   300.1
  745.27   296.7   750.7  296.57 1285.04  296.14 1344.89  297.44 1473.79  296.22
 2046.78  296.06 2093.85  297.13 2212.51     296 2534.07   298.3 2644.28  301.09
 2663.27  300.83 2766.85  304.09 2818.55  304.67 2831.12  305.69 2901.26     306
#Mann= 3 , 0 , 0
       0    .035       0  670.02     .03       0  701.47      .1       0
Bank Sta=670.02,701.47
XS Rating Curve= 0 ,0
Exp/Cntr=0.3,0.1

Type RM Length L Ch R = 1 ,0.13    ,119.5,119.51,119.5
XS GIS Cut Line= 3
   943637.152646  424240.3162534  945475.8734474   425031.442915
  946649.4179144  425527.9685264
#Sta/Elev= 30
       0  308.28  225.23  306.66   326.3  308.32  533.21  307.94  583.31   306.6
  604.14  307.68  739.47  304.57  967.13  296.59  999.14  296.73 1005.33  290.14
 1011.18  288.86 1018.27  289.96 1025.22  294.16 1040.73  296.98 1072.13  298.35
 1088.76  295.26 1096.52  297.57 1476.22  295.26 1656.49  295.61 1693.71  297.17
  1726.9  295.79    2007  296.54 2139.04  295.28 2300.63  295.54 2365.66  297.16
 2381.44   295.8 2396.09  296.79 2486.64   295.6 2866.02  298.48 3275.96  306.82
#Mann= 3 , 0 , 0
       0    .035       0  999.14     .03       0 1040.73      .1       0
Bank Sta=999.14,1040.73
XS Rating Curve= 0 ,0
Exp/Cntr=0.3,0.1

Type RM Length L Ch R = 1 ,0.10    ,770,710,610
XS GIS Cut Line= 3
  943585.7226802    424350.75119  945423.0667329  425134.7853974
  946601.4501164  425607.3151291
#Sta/Elev= 30
       0  305.82   82.78  307.09  238.67  305.77  494.45   305.9  722.04   302.8
  752.73  301.46  837.69   301.9  947.12  297.88  986.14  298.39  995.53  296.48
 1010.31  296.62 1018.65  289.98 1029.38  288.77 1038.27  289.87 1040.97  296.93
 1056.25  298.44 1120.29  296.95 1133.15  295.57 1156.11  296.76 1810.58  296.03
 1890.21  296.23 1895.72  297.29 2001.07     296 2116.86  296.67 2258.56  295.66
 2637.94  296.46 2762.59  298.99 2931.94  299.74 3007.83  302.12 3267.23  306.53
#Mann= 3 , 0 , 0
       0    .035       0 1010.31     .03       0 1040.97      .1       0
Bank Sta=1010.31,1040.97
XS Rating Curve= 0 ,0
Exp/Cntr=0.3,0.1

--- Haywood213.g03 (geometry) ---

Geom Title=Diversion
Program Version=4.10

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
River Reach=Stream          ,Reach

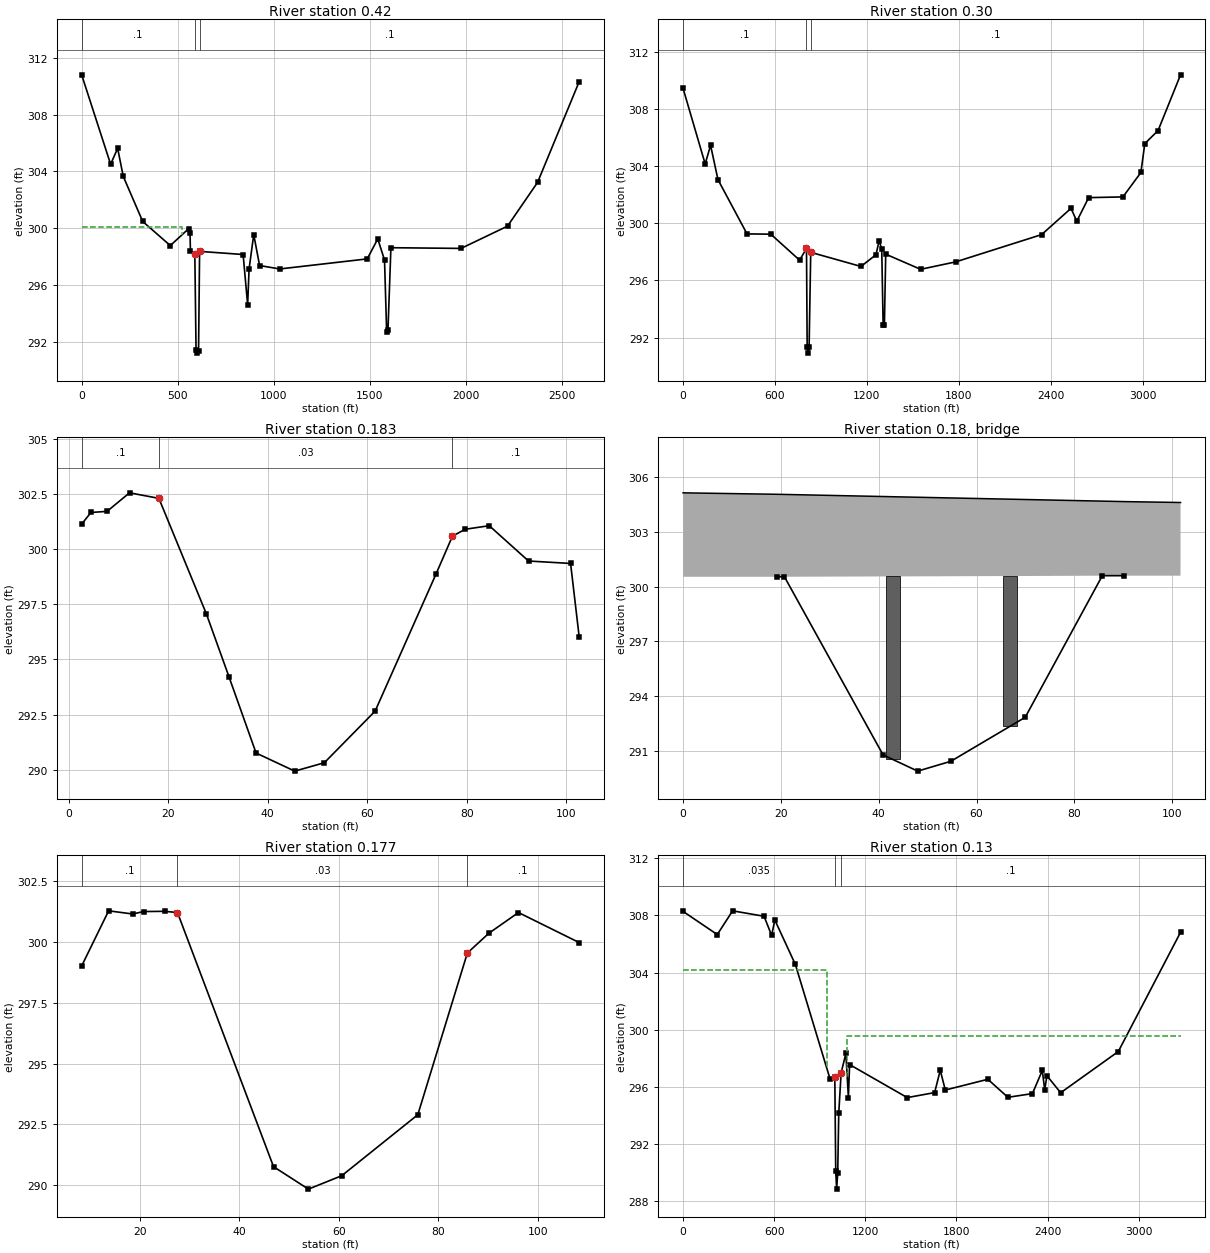
Type RM Length L Ch R = 1 ,0.42    ,420,633,608
XS GIS Cut Line= 2
       944568.11       423843.76       944641.97       423856.78
#Sta/Elev= 30
       0  310.82   150.8  304.51   187.5  305.63  216.75  303.65  318.08  300.47
  461.85  298.77  558.07  299.97  564.52  299.65  566.68  298.38  589.58  298.17
  595.99  291.37  601.13  291.18  608.99  291.32  614.44  298.36  841.17  298.14
  864.78  294.59  872.23  297.12  896.48  299.55  927.01  297.36 1032.23  297.12
 1487.73  297.83 1542.71  299.24 1577.91  297.75 1588.96   292.7 1595.86  292.82
 1611.22  298.62 1976.48  298.57 2218.62  300.14  2375.3  303.23 2591.86  310.33
#Mann= 3 , 0 , 0
       0      .1       0  589.58     .03       0  614.44      .1       0
#XS Ineff= 2 , 0
       0  522.33  300.06  896.48       0  299.55
Permanent Ineff=
       F       F
Bank Sta=589.58,614.44
XS Rating Curve= 0 ,0
Exp/Cntr=0.3,0.1

Type RM Length L Ch R = 1 ,0.30    ,360,620,390
XS GIS Cut Line= 2
       944752.46       424111.34       944788.41       424196.03
#Sta/Elev= 30
       0  309.45  144.26  304.16  179.68  305.46  227.85  303.06  417.51  299.26
  572.86  299.24  760.73  297.42  805.88  298.24  810.28  291.32  817.68  290.91
  822.83  291.33  833.56  297.97 1161.51  296.98  1259.6   297.8 1280.25  298.79
 1297.14  298.19 1306.37  292.86 1314.55  292.89 1323.16  297.84 1550.95  296.78
 1779.91   297.3 2341.02  299.21    2533  301.05 2570.79  300.15 2648.15   301.8
 2871.93  301.85 2989.33  303.56 3014.61  305.58  3101.5   306.5  3248.1   310.4
#Mann= 3 , 0 , 0
       0      .1       0  805.88     .03       0  833.56      .1       0
#XS Ineff= 2 , 0
       0  572.86  299.24  833.56       0  297.97
Permanent Ineff=
       F       F
Bank Sta=805.88,833.56
XS Rating Curve= 0 ,0
Exp/Cntr=0.3,0.1

Type RM Length L Ch R = 1 ,0.183   ,34,34,34
XS GIS Cut Line= 2
       944741.29       424444.77       944831.17        424488.6
#Sta/Elev= 18
    2.61  301.13    4.47  301.66    7.71  301.71   12.23  302.55   18.13   302.3
   27.67  297.07   32.23  294.21   37.67  290.76   45.44  289.94   51.39  290.32
    61.6  292.66   73.84  298.87   77.15  300.59   79.73   300.9   84.54  301.06
   92.44  299.46  100.89  299.35  102.61  296.04
#Mann= 3 , 0 , 0
    2.61      .1       0   18.13     .03       0   77.15      .1       0
#XS Ineff= 2 , 0
       0   10.22            96.2       0
Permanent Ineff=
       F       F
Bank Sta=18.13,77.15
XS Rating Curve= 0 ,0
Exp/Cntr=0.5,0.3

Type RM Length L Ch R = 3 ,0.18    ,,,
Bridge Culvert--1,0,-1,-1, 0
Deck Dist Width WeirC Skew NumUp NumDn MinLoCord MaxHiCord MaxSubmerge Is_Ogee
10.5,14,2.6,0, 4, 4, , , 0.98, 0, 0,0,,
       0   19.26   90.18  101.69
  305.14  305.06  304.66  304.61
          300.54   300.6
       0   19.26   90.18  101.69
  305.14  305.06  304.66  304.61
          300.54   300.6
Pier Skew, UpSta & Num, DnSta & Num=  ,42.89, 4 ,42.89, 4 , 3 , 3 , 0 ,,
    1.08    1.08     2.8     2.8
     290  297.35  297.35     301
    1.08    1.08     2.8     2.8
     290  297.35  297.35     301
Pier Skew, UpSta & Num, DnSta & Num=  ,66.89, 4 ,66.89, 4 , 3 , 3 , 0 ,,
    1.08    1.08     2.8     2.8
     290  297.35  297.35     301
    1.08    1.08     2.8     2.8
     290  297.35  297.35     301
BR Coef=-1 , 1 , 1 ,0.9, 0 ,,,0.8,0,1.2,0,
WSPro=,,,, 1 ,,,, 0 ,,,, 0 ,,,,-1 ,-1 ,-1 , 0 , 0 , 0 , 0 , 0
BR U #Sta/Elev= 8
   19.26  300.54   20.72  300.54   40.88  290.78   47.96  289.89   54.74  290.43
   69.94  292.84    85.7   300.6   90.18   300.6
BR U #Mann= 1
   19.26    .035
BR U Banks=20.72,85.7
BR D #Sta/Elev= 8
   19.26  300.54   20.72  300.54   40.88  290.78   47.96  289.89   54.74  290.43
   69.94  292.84    85.7   300.6   90.18   300.6
BR D #Mann= 1
   19.26    .035
BR D Banks=20.72,85.7
BC Design=,, 0 ,, 0 ,,,,,,
BC Use User HTab Curves=0
BC User HTab FreeFlow(D)= 0

Type RM Length L Ch R = 1 ,0.177   ,115,140,162
XS GIS Cut Line= 2
       944721.18       424473.04       944811.06       424513.88
#Sta/Elev= 14
    8.28     299    13.7  301.26   18.55  301.13   20.71  301.23   24.95  301.24
   27.54  301.19   46.85  290.77   53.86  289.85   60.56   290.4   75.85   292.9
   85.81  299.53   90.13  300.34   96.08  301.19  108.28  299.96
#Mann= 3 , 0 , 0
    8.28      .1       0   27.54     .03       0   85.81      .1       0
#XS Ineff= 2 , 0
       0    13.7           96.08       0
Permanent Ineff=
       F       F
Bank Sta=27.54,85.81
XS Rating Curve= 0 ,0
Exp/Cntr=0.5,0.3

Type RM Length L Ch R = 1 ,0.13    ,119.5,119.51,119.5
XS GIS Cut Line= 3
   943637.152646  424240.3162534  945475.8734474   425031.442915
  946649.4179144  425527.9685264
#Sta/Elev= 30
       0  308.28  225.23  306.66   326.3  308.32  533.21  307.94  583.31   306.6
  604.14  307.68  739.47  304.57  967.13  296.59  999.14  296.73 1005.33  290.14
 1011.18  288.86 1018.27  289.96 1025.22  294.16 1040.73  296.98 1072.13  298.35
 1088.76  295.26 1096.52  297.57 1476.22  295.26 1656.49  295.61 1693.71  297.17
  1726.9  295.79    2007  296.54 2139.04  295.28 2300.63  295.54 2365.66  297.16
 2381.44   295.8 2396.09  296.79 2486.64   295.6 2866.02  298.48 3275.96  306.82
#Mann= 3 , 0 , 0
       0    .035       0  999.14     .03       0 1040.73      .1       0
#XS Ineff= 2 , 0
       0     948   304.2    1081       0   299.6
Permanent Ineff=
       F       F
Bank Sta=999.14,1040.73
XS Rating Curve= 0 ,0
Exp/Cntr=0.5,0.3

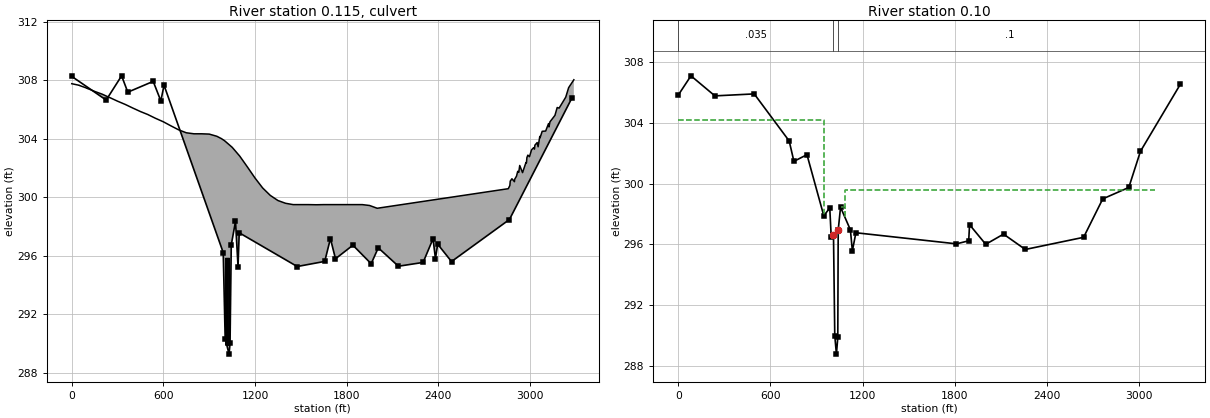
Type RM Length L Ch R = 2 ,0.115   ,,,
Bridge Culvert--1,-1,-1,-1, 0
Deck Dist Width WeirC Skew NumUp NumDn MinLoCord MaxHiCord MaxSubmerge Is_Ogee
29,37.25,2.6,0, 106, 106, , , 0.98, 0, 0,0,,
       0   49.51   49.73  100.23  100.32   100.4  123.16  150.52  200.03  200.09
  249.82  250.32  250.83  300.43   300.6  350.26  400.24  400.28  400.31  450.34
  500.26  500.29  503.38  550.32  550.76     600     650     700     750     800
     850     900     950  979.78  979.78    1000 1049.78 1049.78    1050    1100
    1150    1200    1250    1300    1350    1400 1400.33 1449.61 1450.25  1500.1
 1500.27 1550.15 1550.31 1600.19 1600.33 1650.18 1650.28 1650.39 1701.64 1701.72
 1720.98 1750.34 1750.47  1800.5 1800.96 1850.33 1850.56 1901.62 1902.19 1949.92
    2000 2858.28 2868.64 2871.26 2882.16 2898.78 2899.94 2912.22 2920.15 2926.88
 2933.28 2951.74 2973.95 2977.34 2980.24 2986.58 2997.12 3010.55 3024.19 3029.79
 3032.53 3047.57 3053.63 3064.69 3066.35  3080.4 3103.22 3121.89 3124.87 3131.28
 3163.83 3178.69 3191.32 3234.62 3253.57 3287.69
  307.78  307.67  307.66  307.47  307.46  307.46  307.37  307.25  307.06  307.06
  306.82  306.82  306.82  306.58  306.58  306.36  306.11  306.11  306.11  305.87
  305.66  305.66  305.64   305.4   305.4  305.17  304.89  304.62  304.42  304.35
  304.35  304.33  304.18  304.02  304.02  303.88  303.43  303.43  303.43  302.82
  302.08  301.32  300.64  300.13  299.78  299.59  299.59   299.5   299.5   299.5
   299.5   299.5   299.5  299.49  299.49   299.5   299.5   299.5   299.5   299.5
   299.5   299.5   299.5   299.5   299.5   299.5   299.5   299.5   299.5  299.44
  299.25  300.59  300.81  301.11  301.27  301.07  301.23  301.45  301.78  301.71
  302.18  301.69  302.38  302.36  302.72  302.89  302.78  303.25   303.4   303.3
  303.57  303.75  303.46  304.17  304.08  304.52  304.54  305.05  304.82  305.17
  305.61  306.15  306.11  306.86  307.51  308.05
                                                                                
                                                                                
                                                                                
                                                                                
                                                                                
                                                                                
                                                                                
                                                                                
                                                                                
                                                                                
                                                
       0   49.51   49.73  100.23  100.32   100.4  123.16  150.52  200.03  200.09
  249.82  250.32  250.83  300.43   300.6  350.26  400.24  400.28  400.31  450.34
  500.26  500.29  503.38  550.32  550.76     600     650     700     750     800
     850     900     950  979.78  979.78    1000 1049.78 1049.78    1050    1100
    1150    1200    1250    1300    1350    1400 1400.33 1449.61 1450.25  1500.1
 1500.27 1550.15 1550.31 1600.19 1600.33 1650.18 1650.28 1650.39 1701.64 1701.72
 1720.98 1750.34 1750.47  1800.5 1800.96 1850.33 1850.56 1901.62 1902.19 1949.92
    2000 2858.28 2868.64 2871.26 2882.16 2898.78 2899.94 2912.22 2920.15 2926.88
 2933.28 2951.74 2973.95 2977.34 2980.24 2986.58 2997.12 3010.55 3024.19 3029.79
 3032.53 3047.57 3053.63 3064.69 3066.35  3080.4 3103.22 3121.89 3124.87 3131.28
 3163.83 3178.69 3191.32 3234.62 3253.57 3287.69
  307.78  307.67  307.66  307.47  307.46  307.46  307.37  307.25  307.06  307.06
  306.82  306.82  306.82  306.58  306.58  306.36  306.11  306.11  306.11  305.87
  305.66  305.66  305.64   305.4   305.4  305.17  304.89  304.62  304.42  304.35
  304.35  304.33  304.18  304.02  304.02  303.88  303.43  303.43  303.43  302.82
  302.08  301.32  300.64  300.13  299.78  299.59  299.59   299.5   299.5   299.5
   299.5   299.5   299.5  299.49  299.49   299.5   299.5   299.5   299.5   299.5
   299.5   299.5   299.5   299.5   299.5   299.5   299.5   299.5   299.5  299.44
  299.25  300.59  300.81  301.11  301.27  301.07  301.23  301.45  301.78  301.71
  302.18  301.69  302.38  302.36  302.72  302.89  302.78  303.25   303.4   303.3
  303.57  303.75  303.46  304.17  304.08  304.52  304.54  305.05  304.82  305.17
  305.61  306.15  306.11  306.86  307.51  308.05
                                                                                
                                                                                
                                                                                
                                                                                
                                                                                
                                                                                
                                                                                
                                                                                
                                                                                
                                                                                
                                                
BR Coef=-1 , 1 , 0 ,1.25, 0 ,,,0.8,0,2,0,
WSPro=,,,, 1 ,,,, 0 ,,,, 0 ,,,,-1 ,-1 ,-1 , 0 , 0 , 0 , 0 , 0
Multiple Barrel Culv=1,6,,60,0.022,0.2,1,1,1,289.85,289.5, 4,Culvert #1  , 0 ,25
    1010    1010    1017    1017    1024    1024    1031    1031
Culvert Bottom n=0.022
BR U #Sta/Elev= 30
       0  308.28  225.23  306.66   326.3  308.32  366.91   307.2  533.21  307.94
  583.31   306.6  604.14  307.68  991.83  296.21 1004.51  290.32 1029.98  289.26
 1036.38  289.99 1044.44  296.74 1072.13  298.35 1088.76  295.26 1096.52  297.57
 1476.22  295.26 1656.49  295.61 1693.71  297.17  1726.9  295.79 1840.89  296.72
 1960.51  295.45    2007  296.54 2139.04  295.28 2300.63  295.54 2365.66  297.16
 2381.44   295.8 2396.09  296.79 2486.64   295.6 2866.02  298.48 3275.96  306.82
BR U #Mann= 3
       0     .04  991.83    .035 1044.44      .1
BR U Banks=991.83,1044.44
BR D #Sta/Elev= 30
       0  305.82   82.78  307.09  238.67  305.77  494.45   305.9  752.73  301.46
  837.69   301.9  947.12  297.88  983.07  298.19  983.37  296.67  991.83  296.21
 1004.51  290.32 1014.51  290.32 1029.98  289.26 1036.38  289.99 1044.44  296.74
  1046.8  297.12 1066.35  298.32 1120.29  296.95 1133.15  295.57 1156.11  296.76
 1810.58  296.03 1890.21  296.23 1895.72  297.29 2001.07     296 2258.56  295.66
 2637.94  296.46 2762.59  298.99 2931.94  299.74 3007.83  302.12 3267.23  306.53
BR D #Mann= 3
       0     .04 1014.51    .035  1046.8      .1
BR D Banks=991.83,1044.44
BC Design=,, 0 ,, 0 ,,,,,,
BC Use User HTab Curves=0
BC User HTab FreeFlow(D)= 0

Type RM Length L Ch R = 1 ,0.10    ,770,710,610
XS GIS Cut Line= 3
  943585.7226802    424350.75119  945423.0667329  425134.7853974
  946601.4501164  425607.3151291
#Sta/Elev= 30
       0  305.82   82.78  307.09  238.67  305.77  494.45   305.9  722.04   302.8
  752.73  301.46  837.69   301.9  947.12  297.88  986.14  298.39  995.53  296.48
 1010.31  296.62 1018.65  289.98 1029.38  288.77 1038.27  289.87 1040.97  296.93
 1056.25  298.44 1120.29  296.95 1133.15  295.57 1156.11  296.76 1810.58  296.03
 1890.21  296.23 1895.72  297.29 2001.07     296 2116.86  296.67 2258.56  295.66
 2637.94  296.46 2762.59  298.99 2931.94  299.74 3007.83  302.12 3267.23  306.53
#Mann= 3 , 0 , 0
       0    .035       0 1010.31     .03       0 1040.97      .1       0
#XS Ineff= 3 ,-1
       0     946   304.2 1056.25    1084  298.44    1084    3100   299.6
Permanent Ineff=
       T       F       T
Bank Sta=1010.31,1040.97
XS Rating Curve= 0 ,0
Exp/Cntr=0.5,0.3

--- Haywood213.g07 (geometry) ---

Geom Title=Existing
Program Version=4.10

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
River Reach=Stream          ,Reach