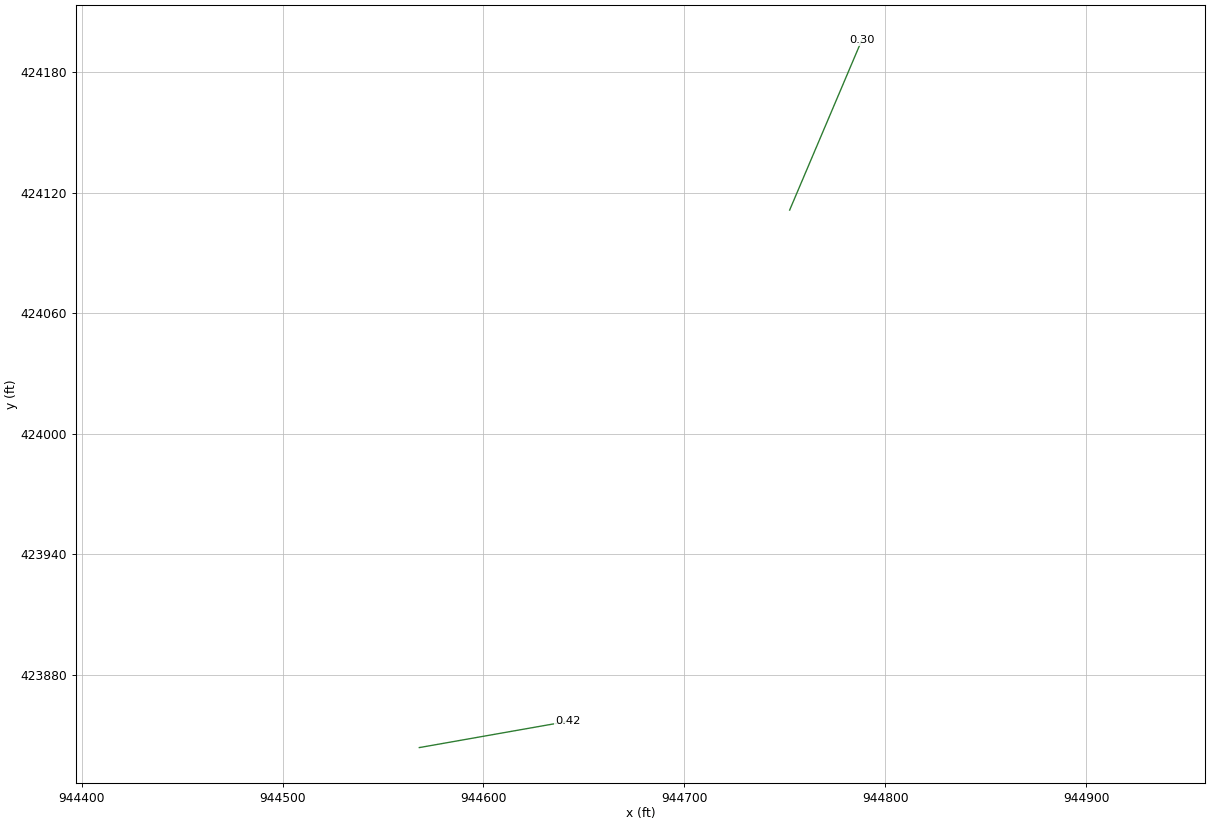
HEC-RAS study Haywood213.prj: Haywood213

--- Haywood213.g07 (geometry) --- (continued)

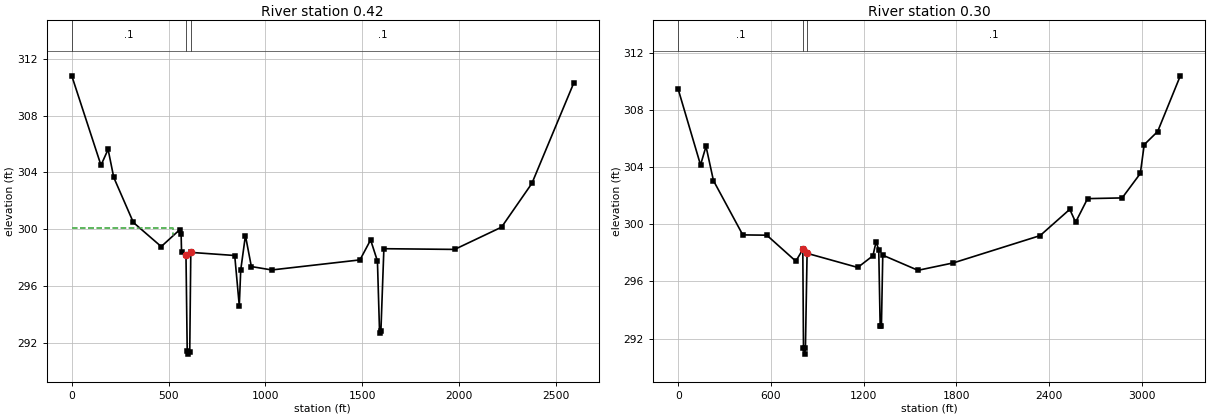
Type RM Length L Ch R = 1 ,0.42    ,420,633,608
XS GIS Cut Line= 2
       944568.11       423843.76       944641.97       423856.78
#Sta/Elev= 30
       0  310.82   150.8  304.51   187.5  305.63  216.75  303.65  318.08  300.47
  461.85  298.77  558.07  299.97  564.52  299.65  566.68  298.38  589.58  298.17
  595.99  291.37  601.13  291.18  608.99  291.32  614.44  298.36  841.17  298.14
  864.78  294.59  872.23  297.12  896.48  299.55  927.01  297.36 1032.23  297.12
 1487.73  297.83 1542.71  299.24 1577.91  297.75 1588.96   292.7 1595.86  292.82
 1611.22  298.62 1976.48  298.57 2218.62  300.14  2375.3  303.23 2591.86  310.33
#Mann= 3 , 0 , 0
       0      .1       0  589.58     .03       0  614.44      .1       0
#XS Ineff= 2 , 0
       0  522.33  300.06  896.48       0  299.55
Permanent Ineff=
       F       F
Bank Sta=589.58,614.44
XS Rating Curve= 0 ,0
Exp/Cntr=0.3,0.1

Type RM Length L Ch R = 1 ,0.30    ,360,620,390
XS GIS Cut Line= 2
       944752.46       424111.34       944788.41       424196.03
#Sta/Elev= 30
       0  309.45  144.26  304.16  179.68  305.46  227.85  303.06  417.51  299.26
  572.86  299.24  760.73  297.42  805.88  298.24  810.28  291.32  817.68  290.91
  822.83  291.33  833.56  297.97 1161.51  296.98  1259.6   297.8 1280.25  298.79
 1297.14  298.19 1306.37  292.86 1314.55  292.89 1323.16  297.84 1550.95  296.78
 1779.91   297.3 2341.02  299.21    2533  301.05 2570.79  300.15 2648.15   301.8
 2871.93  301.85 2989.33  303.56 3014.61  305.58  3101.5   306.5  3248.1   310.4
#Mann= 3 , 0 , 0
       0      .1       0  805.88     .03       0  833.56      .1       0
#XS Ineff= 2 , 0
       0  572.86  299.24  833.56       0  297.97
Permanent Ineff=
       F       F
Bank Sta=805.88,833.56
XS Rating Curve= 0 ,0
Exp/Cntr=0.3,0.1