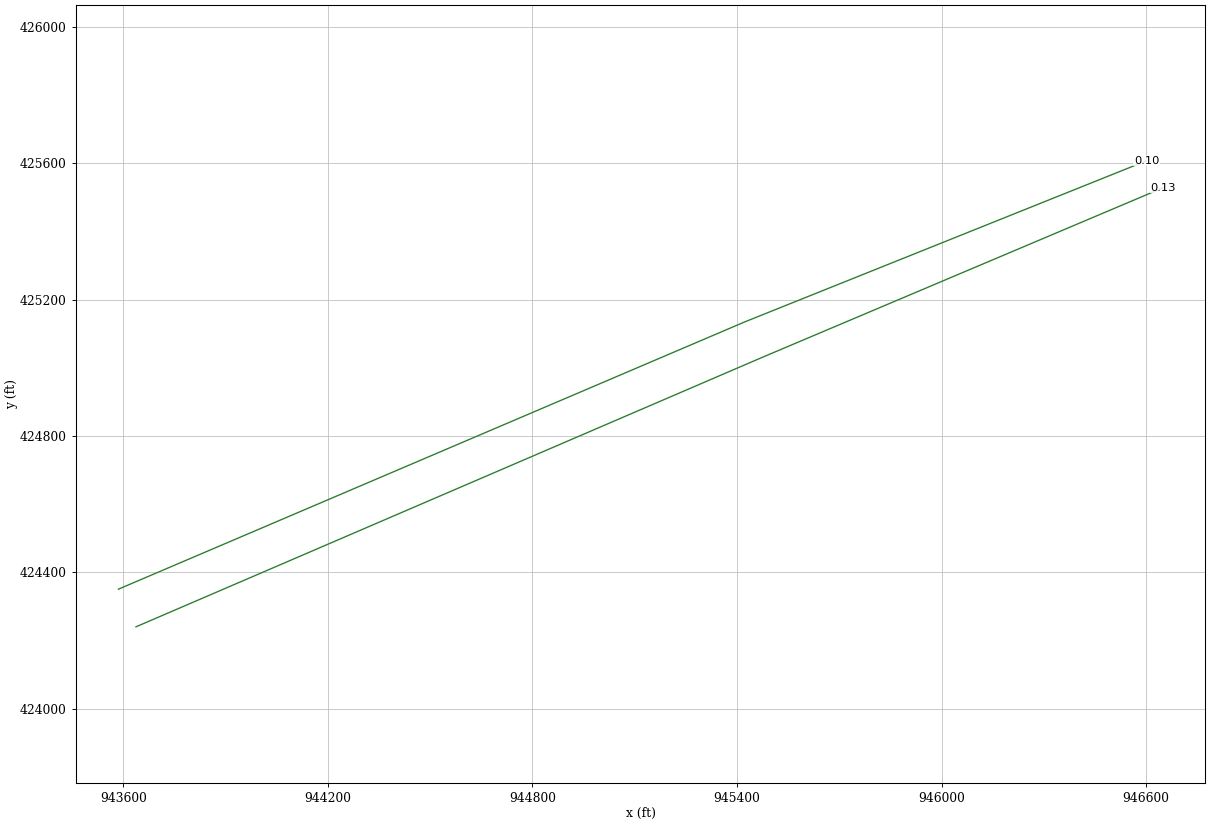
HEC-RAS study Haywood213.prj: Haywood213

--- Haywood213.g07 (geometry) --- (continued)

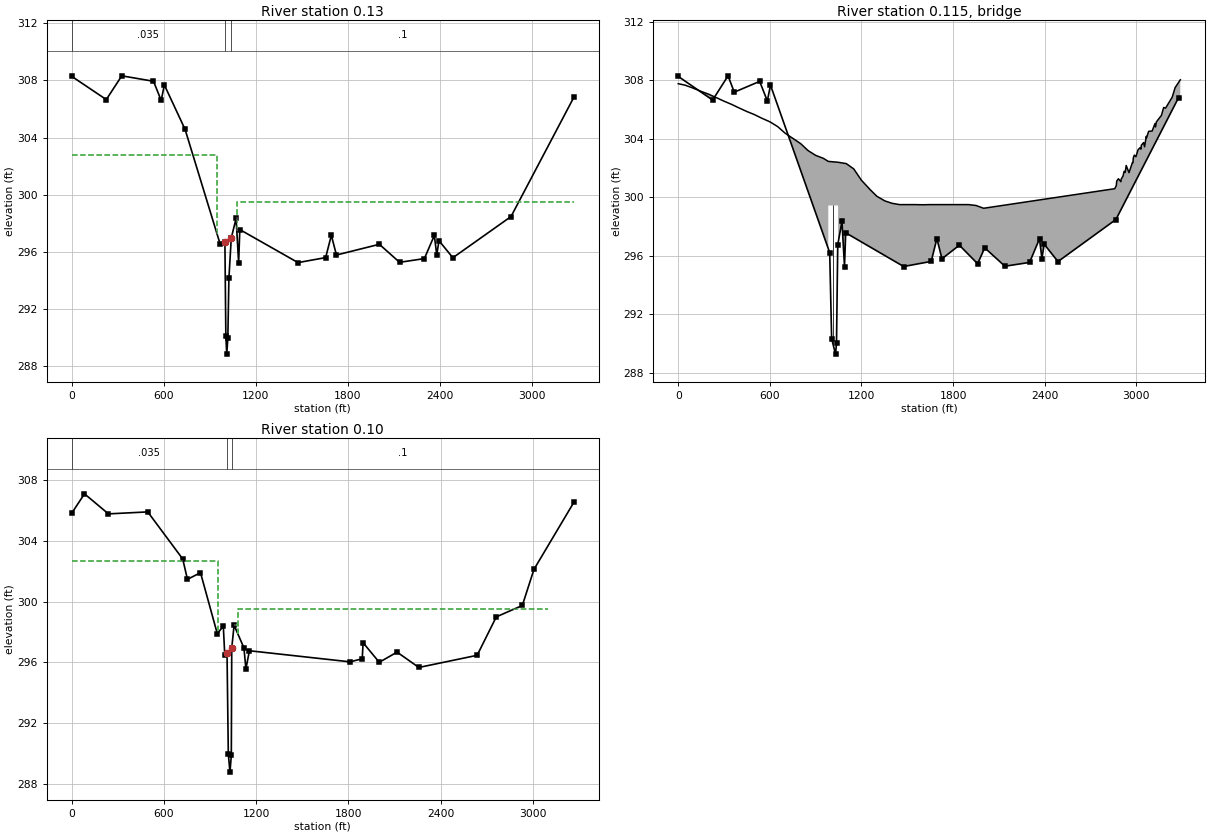
Type RM Length L Ch R = 1 ,0.13    ,119.5,119.51,119.5
XS GIS Cut Line= 3
   943637.152646  424240.3162534  945475.8734474   425031.442915
  946649.4179144  425527.9685264
#Sta/Elev= 30
       0  308.28  225.23  306.66   326.3  308.32  533.21  307.94  583.31   306.6
  604.14  307.68  739.47  304.57  967.13  296.59  999.14  296.73 1005.33  290.14
 1011.18  288.86 1018.27  289.96 1025.22  294.16 1040.73  296.98 1072.13  298.35
 1088.76  295.26 1096.52  297.57 1476.22  295.26 1656.49  295.61 1693.71  297.17
  1726.9  295.79    2007  296.54 2139.04  295.28 2300.63  295.54 2365.66  297.16
 2381.44   295.8 2396.09  296.79 2486.64   295.6 2866.02  298.48 3275.96  306.82
#Mann= 3 , 0 , 0
       0    .035       0  999.14     .03       0 1040.73      .1       0
#XS Ineff= 2 , 0
       0  950.73   302.8    1077       0   299.5
Permanent Ineff=
       F       F
Bank Sta=999.14,1040.73
XS Rating Curve= 0 ,0
Exp/Cntr=0.5,0.3

Type RM Length L Ch R = 3 ,0.115   ,,,
Bridge Culvert--1,-1,-1,-1, 0
Deck Dist Width WeirC Skew NumUp NumDn MinLoCord MaxHiCord MaxSubmerge Is_Ogee
31.5,34.4,2.6,0, 120, 120, , , 0.98, 0, 0,0,,
       0   49.51   49.73  100.23  100.32   100.4  123.16  150.52  200.03  200.09
  249.82  250.32  250.83  300.43   300.6  350.26  400.24  400.28  400.31  450.34
  500.26  500.29  503.38  550.32  550.76   600.3  649.95  650.33  699.98   700.3
  749.64  750.28  799.69  800.28  850.02  850.39   900.2  900.38  950.21  950.31
  958.06  982.73  982.73 1046.83 1046.83 1099.35 1100.03  1149.9 1150.26 1195.64
 1200.27  1200.3 1211.14 1250.21 1250.34 1299.79 1300.31 1300.83 1350.28 1351.16
 1400.33 1449.61 1450.25  1500.1 1500.27 1550.15 1550.31 1600.19 1600.33 1650.18
 1650.28 1650.39 1701.64 1701.72 1720.98 1750.34 1750.47  1800.5 1800.96 1850.33
 1850.56 1901.62 1902.19 1949.92    2000 2858.28 2868.64 2871.26 2882.16 2898.78
 2899.94 2912.22 2920.15 2926.88 2933.28 2951.74 2973.95 2977.34 2980.24 2986.58
 2997.12 3010.55 3024.19 3029.79 3032.53 3047.57 3053.63 3064.69 3066.35  3080.4
 3103.22 3121.89 3124.87 3131.28 3163.83 3178.69 3191.32 3234.62 3253.57 3287.69
  307.78  307.67  307.66  307.47  307.46  307.46  307.37  307.25  307.06  307.06
  306.82  306.82  306.82  306.58  306.58  306.36  306.11  306.11  306.11  305.87
  305.66  305.66  305.64   305.4   305.4  305.17  304.85  304.85  304.39  304.39
  304.04  304.04  303.69  303.69   303.2   303.2  302.87  302.87  302.67  302.67
  302.62  302.46  302.46   302.4   302.4  302.31  302.31  301.94  301.93  301.23
  301.16  301.16  301.04   300.6  300.59  300.08  300.08  300.07  299.77  299.76
  299.59   299.5   299.5   299.5   299.5   299.5   299.5  299.49  299.49   299.5
   299.5   299.5   299.5   299.5   299.5   299.5   299.5   299.5   299.5   299.5
   299.5   299.5   299.5  299.44  299.25  300.59  300.81  301.11  301.27  301.07
  301.23  301.45  301.78  301.71  302.18  301.69  302.38  302.36  302.72  302.89
  302.78  303.25   303.4   303.3  303.57  303.75  303.46  304.17  304.08  304.52
  304.54  305.05  304.82  305.17  305.61  306.15  306.11  306.86  307.51  308.05
                                                                                
                                                                                
                                                                                
                                                                                
               0  299.44  299.44       0
                                                                                
                                                                                
                                                                                
                                                                                
                                                                                
                                                                                
                                                                                
       0   49.51   49.73  100.23  100.32   100.4  123.16  150.52  200.03  200.09
  249.82  250.32  250.83  300.43   300.6  350.26  400.24  400.28  400.31  450.34
  500.26  500.29  503.38  550.32  550.76   600.3  649.95  650.33  699.98   700.3
  749.64  750.28  799.69  800.28  850.02  850.39   900.2  900.38  950.21  950.31
  958.06  982.73  982.73 1046.83 1046.83 1099.35 1100.03  1149.9 1150.26 1195.64
 1200.27  1200.3 1211.14 1250.21 1250.34 1299.79 1300.31 1300.83 1350.28 1351.16
 1400.33 1449.61 1450.25  1500.1 1500.27 1550.15 1550.31 1600.19 1600.33 1650.18
 1650.28 1650.39 1701.64 1701.72 1720.98 1750.34 1750.47  1800.5 1800.96 1850.33
 1850.56 1901.62 1902.19 1949.92    2000 2858.28 2868.64 2871.26 2882.16 2898.78
 2899.94 2912.22 2920.15 2926.88 2933.28 2951.74 2973.95 2977.34 2980.24 2986.58
 2997.12 3010.55 3024.19 3029.79 3032.53 3047.57 3053.63 3064.69 3066.35  3080.4
 3103.22 3121.89 3124.87 3131.28 3163.83 3178.69 3191.32 3234.62 3253.57 3287.69
  307.78  307.67  307.66  307.47  307.46  307.46  307.37  307.25  307.06  307.06
  306.82  306.82  306.82  306.58  306.58  306.36  306.11  306.11  306.11  305.87
  305.66  305.66  305.64   305.4   305.4  305.17  304.85  304.85  304.39  304.39
  304.04  304.04  303.69  303.69   303.2   303.2  302.87  302.87  302.67  302.67
  302.62  302.46  302.46   302.4   302.4  302.31  302.31  301.94  301.93  301.23
  301.16  301.16  301.04   300.6  300.59  300.08  300.08  300.07  299.77  299.76
  299.59   299.5   299.5   299.5   299.5   299.5   299.5  299.49  299.49   299.5
   299.5   299.5   299.5   299.5   299.5   299.5   299.5   299.5   299.5   299.5
   299.5   299.5   299.5  299.44  299.25  300.59  300.81  301.11  301.27  301.07
  301.23  301.45  301.78  301.71  302.18  301.69  302.38  302.36  302.72  302.89
  302.78  303.25   303.4   303.3  303.57  303.75  303.46  304.17  304.08  304.52
  304.54  305.05  304.82  305.17  305.61  306.15  306.11  306.86  307.51  308.05
                                                                                
                                                                                
                                                                                
                                                                                
               0  299.44  299.44       0
                                                                                
                                                                                
                                                                                
                                                                                
                                                                                
                                                                                
                                                                                
Pier Skew, UpSta & Num, DnSta & Num=  ,1014.51, 4 ,1014.51, 4 , 3 , 3 , 0 ,,
     2.5     2.5    2.75    2.75
       0  298.44  298.44  299.44
     2.5     2.5    2.75    2.75
       0  298.44  298.44  299.44
BR Coef=-1 , 1 , 1 ,1.25, 0 ,,,0.8,0,2,0,
WSPro=,,,, 1 ,,,, 0 ,,,, 0 ,,,,-1 ,-1 ,-1 , 0 , 0 , 0 , 0 , 0
BR U #Sta/Elev= 30
       0  308.28  225.23  306.66   326.3  308.32  366.91   307.2  533.21  307.94
  583.31   306.6  604.14  307.68  991.83  296.21 1004.51  290.32 1029.98  289.26
 1036.38  289.99 1044.44  296.74 1072.13  298.35 1088.76  295.26 1096.52  297.57
 1476.22  295.26 1656.49  295.61 1693.71  297.17  1726.9  295.79 1840.89  296.72
 1960.51  295.45    2007  296.54 2139.04  295.28 2300.63  295.54 2365.66  297.16
 2381.44   295.8 2396.09  296.79 2486.64   295.6 2866.02  298.48 3275.96  306.82
BR U #Mann= 3
       0     .04  991.83    .035 1044.44      .1
BR U Banks=991.83,1044.44
BR D #Sta/Elev= 30
       0  305.82   82.78  307.09  238.67  305.77  494.45   305.9  752.73  301.46
  837.69   301.9  947.12  297.88  983.07  298.19  983.37  296.67  991.83  296.21
 1004.51  290.32 1014.51  290.32 1029.98  289.26 1036.38  289.99 1044.44  296.74
  1046.8  297.12 1066.35  298.32 1120.29  296.95 1133.15  295.57 1156.11  296.76
 1810.58  296.03 1890.21  296.23 1895.72  297.29 2001.07     296 2258.56  295.66
 2637.94  296.46 2762.59  298.99 2931.94  299.74 3007.83  302.12 3267.23  306.53
BR D #Mann= 3
       0     .04 1014.51    .035  1046.8      .1
BR D Banks=991.83,1044.44
BC Design=,, 0 ,, 0 ,,,,,,
BC Use User HTab Curves=0
BC User HTab FreeFlow(D)= 0

Type RM Length L Ch R = 1 ,0.10    ,770,710,610
XS GIS Cut Line= 3
  943585.7226802    424350.75119  945423.0667329  425134.7853974
  946601.4501164  425607.3151291
#Sta/Elev= 30
       0  305.82   82.78  307.09  238.67  305.77  494.45   305.9  722.04   302.8
  752.73  301.46  837.69   301.9  947.12  297.88  986.14  298.39  995.53  296.48
 1010.31  296.62 1018.65  289.98 1029.38  288.77 1038.27  289.87 1040.97  296.93
 1056.25  298.44 1120.29  296.95 1133.15  295.57 1156.11  296.76 1810.58  296.03
 1890.21  296.23 1895.72  297.29 2001.07     296 2116.86  296.67 2258.56  295.66
 2637.94  296.46 2762.59  298.99 2931.94  299.74 3007.83  302.12 3267.23  306.53
#Mann= 3 , 0 , 0
       0    .035       0 1010.31     .03       0 1040.97      .1       0
#XS Ineff= 3 ,-1
       0     950   302.7 1056.25    1080  298.44    1080    3100   299.5
Permanent Ineff=
       T       F       F
Bank Sta=1010.31,1040.97
XS Rating Curve= 0 ,0
Exp/Cntr=0.5,0.3